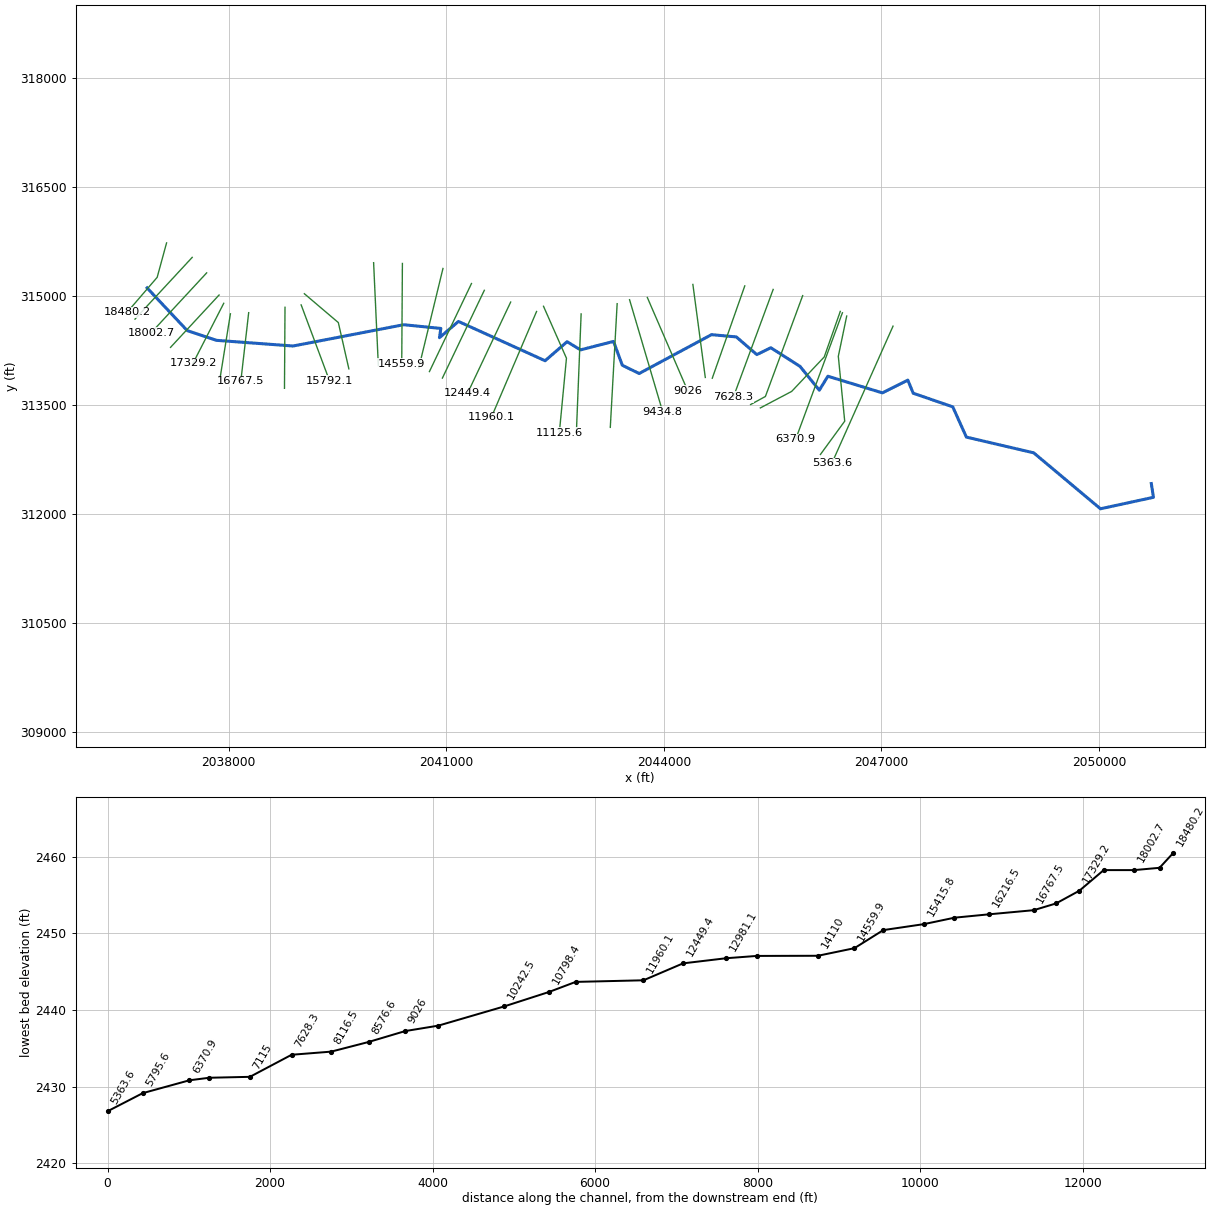
--- BuffaloCk.prj (project) ---

Proj Title=BuffaloCk
Current Plan=p01
Default Exp/Contr=0,0
English Units
Geom File=g01
Flow File=f01
Plan File=p01
BEGIN DESCRIPTION:
END DESCRIPTION:
DSS Export Rating Curves= 0
DSS Export Rating Curve Sorted= 0
DSS Export Volume Flow Curves= 0
DXF OffsetX= 0
DXF OffsetY= 0
DXF ScaleX= 0
DXF ScaleY= 0

--- BuffaloCk.p01 (plan) ---

Plan Title=Floodplain
Program Version=4.00
Geom File=g01
Flow File=f01
K Sum by GR=0
Std Step Tol=0.01
Critical Tol=0.01
Num of Std Step Trials=20
Max Error Tol=0.3
Flow Tol Ratio=0.001
Split Flow NTrial=30
Split Flow Tol=0.02
Split Flow Ratio=0.02
Log Output Level=0
Friction Slope Method=1
Unsteady Friction Slope Method=2
Unsteady Bridges Friction Slope Method=1
Global Log Level=0
CheckData=False
Run HTab=0
Run UNet=0
Run PostProcess=0
UNET Theta=0
UNET Theta Warmup=0
UNET ZTol=0
UNET ZSATol=0
UNET MxIter=0
UNET MaxInSteps=0
UNET DtIC=0
UNET DtMin=0
UNET MaxCRTS=0
UNET WFStab=0
UNET SFStab=0
UNET WFX=0
UNET SFX=0
UNET DSS MLevel=0
UNET DZMax Abort=0
UNET Convert EG Bridges=0
UNET Use Existing IB Tables=0
UNET Froude Limit=0
UNET Froude Power=0
Write IC File=0
Echo Input=False
Echo Output=False
Write Detailed=0

--- BuffaloCk.f01 (steady flow) ---

Flow Title=NFF Regression Equation
Program Version=4.00
Number of Profiles=1
Profile Names=P100yr
River Rch & RM=BuffaloCk,Main      ,18480.2
631.9794
River Rch & RM=BuffaloCk,Main      ,16767.5
682.6304
River Rch & RM=BuffaloCk,Main      ,16216.5
768.1668
River Rch & RM=BuffaloCk,Main      ,14559.9
812.8129
River Rch & RM=BuffaloCk,Main      ,10242.5
884.0928
River Rch & RM=BuffaloCk,Main      ,9434.8
980.4929
River Rch & RM=BuffaloCk,Main      ,6370.9
1084.900
River Rch & RM=BuffaloCk,Main      ,1448.2
1156.502
Boundary for River Rch & Prof#=BuffaloCk,Main      ,1
Up Type=0
Dn Type=3
Dn Slope=0.001754

--- BuffaloCk.g01 (geometry) ---

Geom Title=USGS 10m DEM
Program Version=4.10

River Reach=BuffaloCk       ,Main
Reach XY= 30
     2036873.163      315113.053     2037426.815      314524.743
     2037830.461      314390.628     2038886.451      314312.503
       2040411.5      314605.739     2040924.211      314554.691
      2040904.68      314427.086     2041166.399      314651.045
     2042361.711      314109.378     2042664.533      314371.588
     2042849.992      314259.118     2043304.908      314375.713
     2043426.347      314046.938     2043658.586      313933.597
     2044655.982      314468.753     2044998.471      314437.716
     2045280.744      314194.185     2045474.166      314288.411
     2045876.944      314031.466     2046142.568      313703.341
     2046260.624       313896.05      2047012.36      313666.883
     2047363.055       313842.23     2047437.708      313661.675
     2047982.846      313474.175     2048170.346      313057.508
     2049099.166      312840.494     2050019.305      312069.661
     2050750.207      312227.647     2050720.693      312416.883

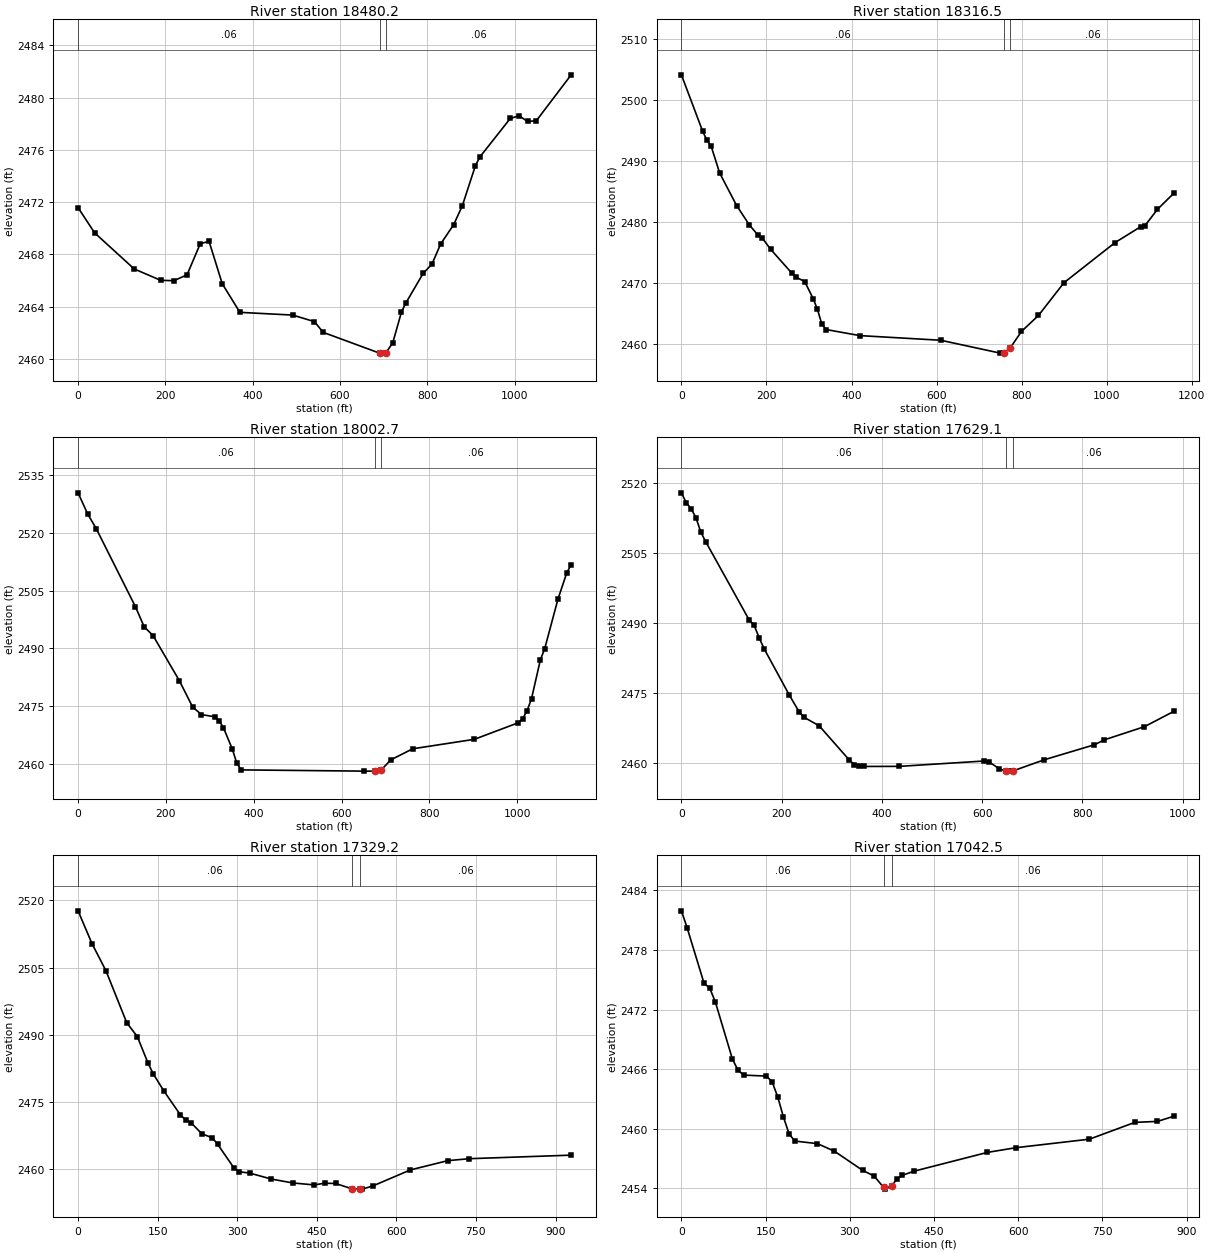
Type RM Length L Ch R = 1 ,18480.2 ,164.9,163.5,162.1
XS GIS Cut Line= 4
     2037141.933       315732.81     2037139.926      315725.464
     2037012.365      315258.646     2036596.254      314775.309
#Sta/Elev= 30
       0 2471.58    37.9 2469.65   128.6 2466.89   189.1 2466.02   219.3 2465.99
   249.6 2466.44   279.8 2468.82     300    2469   330.2 2465.76   370.6 2463.57
   491.6 2463.36   541.4 2462.86   561.3 2462.04   690.5 2460.45   705.5 2460.49
   720.8 2461.25   740.7  2463.6   750.6 2464.28   790.5 2466.56   810.4 2467.25
   830.4  2468.8   860.3 2470.28   880.2 2471.74   910.1  2474.8   920.1 2475.45
   989.8  2478.4  1009.7 2478.61  1029.7 2478.17  1049.6 2478.23  1129.3 2481.74
#Mann= 3 , 0 , 0
       0     .06       0   690.5    .045       0   705.5     .06       0
Bank Sta=690.5,705.5
XS Rating Curve= 0 ,0
Exp/Cntr=0.3,0.1

Type RM Length L Ch R = 1 ,18316.5 ,317.9,314.2,311.4
XS GIS Cut Line= 3
     2037495.226      315533.381     2037372.848      315401.469
     2036706.622      314683.336
#Sta/Elev= 30
       0 2504.18      50 2494.93      60 2493.46      70 2492.47      90 2488.08
     130 2482.74   159.9 2479.57   179.9 2477.93   189.9 2477.46   209.9 2475.58
   259.9 2471.66   269.9 2471.01   289.9  2470.3   309.9 2467.49   319.9 2465.74
   329.9 2463.39   339.9 2462.44   419.8 2461.44   609.8 2460.68   749.7 2458.57
     758 2458.61     773 2459.39   799.7 2462.13   839.6 2464.74   899.6 2470.11
  1019.6 2476.68  1079.6 2479.27  1089.5 2479.41  1119.5 2482.14  1159.5 2484.88
#Mann= 3 , 0 , 0
       0     .06       0     758    .045       0     773     .06       0
Bank Sta=758,773
XS Rating Curve= 0 ,0
Exp/Cntr=0.3,0.1

Type RM Length L Ch R = 1 ,18002.7 ,361.7,373.1,374.5
XS GIS Cut Line= 4
     2037694.593      315319.773      2037679.91      315303.946
     2037598.967      315216.695     2036930.827      314496.499
#Sta/Elev= 30
       0 2530.28    21.6 2524.86    41.4 2521.01   130.7  2500.8   150.6  2495.6
   170.7 2493.36   230.8 2481.65   260.9 2474.86     281  2472.9     311 2472.34
     321 2471.35   331.1 2469.49   351.1 2464.04   361.1 2460.48   371.2 2458.59
   651.8 2458.27   675.2 2458.27   690.2 2458.53     712 2461.17   762.1 2464.05
   902.5  2466.5  1002.7 2470.79  1012.7 2471.85  1022.8 2473.95  1032.8 2477.06
  1052.8 2487.02  1062.8 2489.98  1092.9 2502.76    1113 2509.58    1123 2511.72
#Mann= 3 , 0 , 0
       0     .06       0   675.2    .045       0   690.2     .06       0
Bank Sta=675.2,690.2
XS Rating Curve= 0 ,0
Exp/Cntr=0.3,0.1

Type RM Length L Ch R = 1 ,17629.1 ,293.4,299.7,306
XS GIS Cut Line= 3
     2037865.986      315015.236     2037773.951      314916.029
     2037196.718      314293.824
#Sta/Elev= 30
       0 2517.86     9.7 2515.74    19.3 2514.48      29 2512.55    38.7 2509.47
    48.3 2507.43   135.3 2490.63   145.3 2489.46   155.3 2486.78   165.3 2484.43
   215.2 2474.58   235.2 2470.91   245.2 2469.77   275.1 2467.96     335 2460.65
     345 2459.68     355 2459.32     365 2459.27   434.9 2459.29   604.6 2460.44
   614.6 2460.19   634.6 2458.76   647.2 2458.28   654.6 2458.27   662.2 2458.34
   724.4 2460.71   824.3 2463.92   844.3 2464.98   924.1 2467.79     984 2471.14
#Mann= 3 , 0 , 0
       0     .06       0   647.2    .045       0   662.2     .06       0
Bank Sta=647.2,662.2
XS Rating Curve= 0 ,0
Exp/Cntr=0.3,0.1

Type RM Length L Ch R = 1 ,17329.2 ,280,286.8,294
XS GIS Cut Line= 3
     2037930.215      314901.052     2037902.223      314846.442
     2037506.225      314073.911
#Sta/Elev= 30
       0 2517.66    26.3 2510.33    52.6 2504.28    91.6 2492.74   111.8 2489.58
     132 2483.65   142.1 2481.21   162.3 2477.38   192.6  2472.2   202.7 2471.01
   212.8 2470.41     233 2467.96   253.2 2467.01   263.2 2465.57   293.5 2460.36
   303.6 2459.46   323.8 2459.15   364.2 2457.83   404.6 2456.96     445 2456.52
   465.1  2456.9   485.3 2456.84   516.4 2455.65   531.4 2455.59   535.8 2455.58
     556 2456.31   626.6 2459.87   697.3 2461.94   737.7 2462.37   929.5 2463.16
#Mann= 3 , 0 , 0
       0     .06       0   516.4    .045       0   531.4     .06       0
Bank Sta=516.4,531.4
XS Rating Curve= 0 ,0
Exp/Cntr=0.3,0.1

Type RM Length L Ch R = 1 ,17042.5 ,273.2,275,276.2
XS GIS Cut Line= 2
     2038022.315      314756.265     2037882.673      313888.948
#Sta/Elev= 30
       0 2481.94    10.1 2480.25    40.4 2474.64    50.5 2474.16    60.6 2472.74
    90.9 2467.01     101 2465.88   111.1  2465.4   151.5  2465.3   161.6 2464.72
   171.7 2463.19   181.8 2461.18   191.8 2459.49     202 2458.76   242.3  2458.5
   272.6 2457.74   323.1  2455.8   343.3 2455.24   360.2  2454.1   363.5 2453.92
   375.2 2454.28   383.7 2454.92   393.8 2455.31     414 2455.72   545.3 2457.62
   595.8 2458.09     727 2458.95   807.8 2460.64   848.2 2460.74   878.5 2461.28
#Mann= 3 , 0 , 0
       0     .06       0   360.2    .045       0   375.2     .06       0
Bank Sta=360.2,375.2
XS Rating Curve= 0 ,0
Exp/Cntr=0.3,0.1

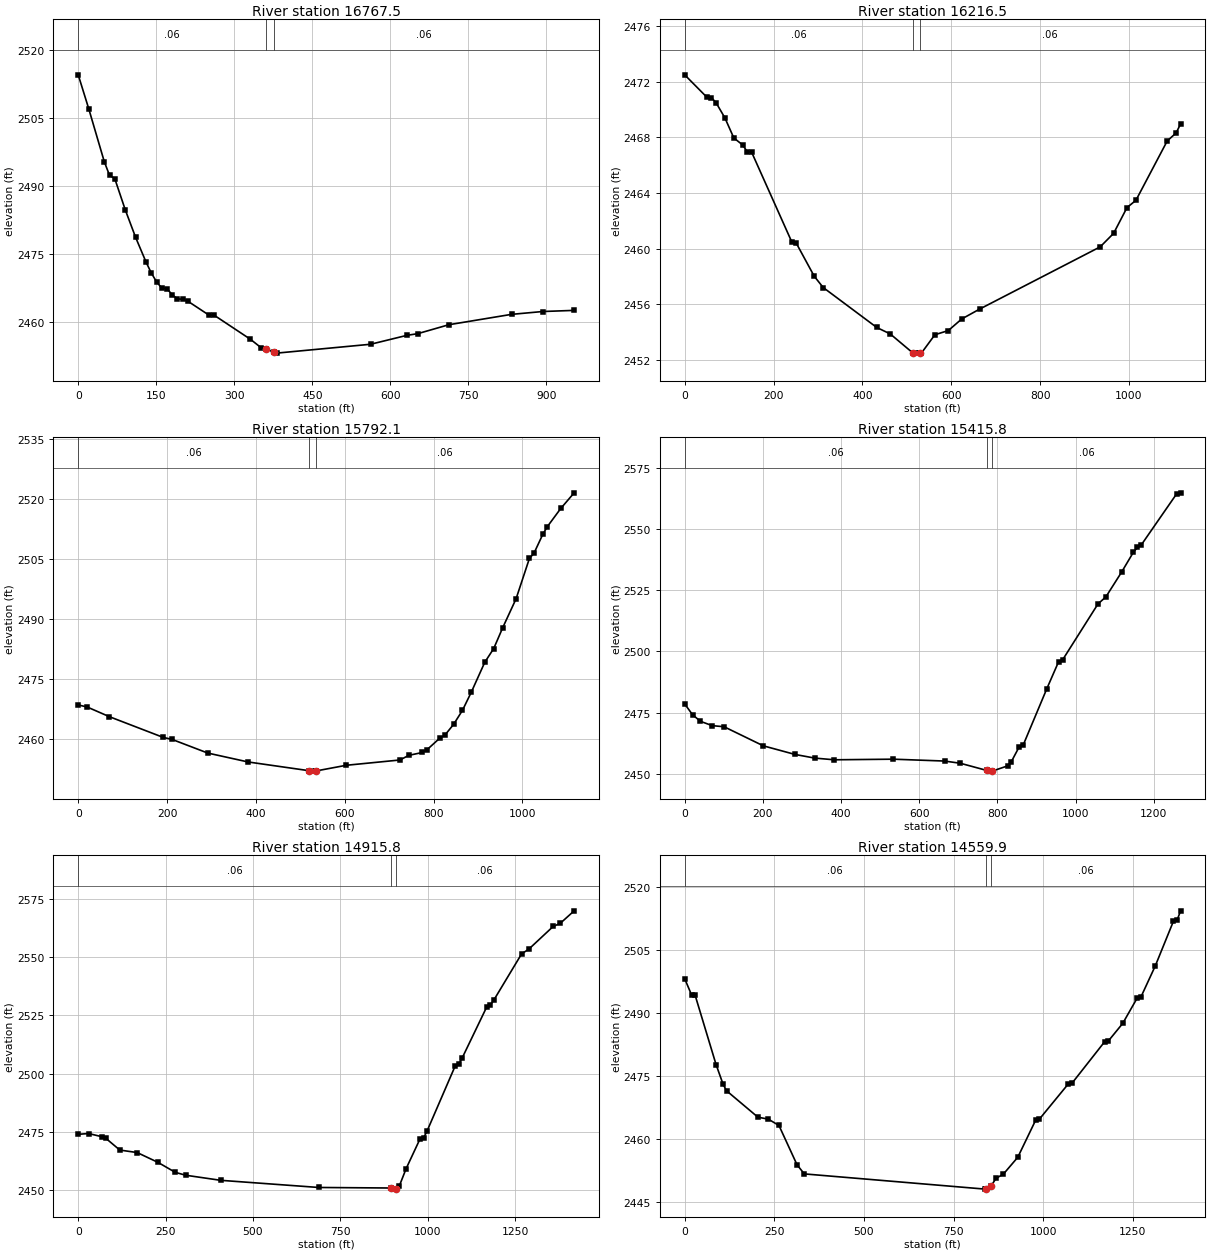
Type RM Length L Ch R = 1 ,16767.5 ,548,550.5,553
XS GIS Cut Line= 2
     2038274.302      314772.014     2038165.668      313825.046
#Sta/Elev= 30
       0 2514.56    20.1 2507.11    50.2 2495.33    60.2 2492.34    70.2 2491.64
    90.3 2484.76   110.4 2478.61   130.4 2473.16   140.5 2470.75   150.5 2468.82
   160.5 2467.41   170.6 2467.32   180.6 2465.93   190.6 2465.04   200.7 2464.94
   210.7 2464.52   250.8 2461.48   260.9 2461.45   331.1 2456.09   351.2 2454.27
   361.1 2454.04   376.1 2453.18   381.3 2453.04   561.9    2455   632.1 2456.98
   652.2 2457.33   712.4 2459.32   832.8 2461.61     893 2462.24   953.2 2462.49
#Mann= 3 , 0 , 0
       0     .06       0   361.1    .045       0   376.1     .06       0
Bank Sta=361.1,376.1
XS Rating Curve= 0 ,0
Exp/Cntr=0.3,0.1

Type RM Length L Ch R = 1 ,16216.5 ,416.6,424.5,432.5
XS GIS Cut Line= 2
     2038775.195      314845.819     2038767.805      313729.533
#Sta/Elev= 30
       0 2472.48    50.3 2470.86    60.3 2470.84    70.4 2470.49    90.5 2469.39
   110.6 2467.95   130.7 2467.44   140.8 2466.96   150.8 2466.92   241.4 2460.46
   251.4 2460.38   291.6 2458.02   311.8 2457.21   432.4 2454.34   462.6 2453.88
   513.7 2452.51     523  2452.5   528.7 2452.51     533 2452.51   563.2 2453.82
   593.4 2454.12   623.5 2454.95   663.8 2455.66   935.3 2460.13   965.5  2461.1
   995.6 2462.95  1015.7 2463.47  1086.1 2467.73  1106.2 2468.31  1116.3 2468.96
#Mann= 3 , 0 , 0
       0     .06       0   513.7    .045       0   528.7     .06       0
Bank Sta=513.7,528.7
XS Rating Curve= 0 ,0
Exp/Cntr=0.3,0.1

Type RM Length L Ch R = 1 ,15792.1 ,379.5,376.4,373.3
XS GIS Cut Line= 2
     2038997.733      314879.165     2039388.982      313833.663
#Sta/Elev= 30
       0 2468.58    20.1 2468.07    70.4 2465.64   191.1 2460.49   211.2 2459.98
   291.6 2456.57   382.2 2454.35   520.1 2452.16     533 2452.06   535.1  2452.1
   603.4 2453.52   724.1 2454.84   744.2    2456   774.4 2456.71   784.4 2457.33
   814.6 2460.37   824.7 2460.96   844.8 2463.71   864.9 2467.23     885 2471.82
   915.2 2479.25   935.3 2482.67   955.4 2487.84   985.6 2495.09  1015.7 2505.19
  1025.8 2506.43  1045.9 2511.21    1056  2513.1  1086.1 2517.62  1116.3 2521.53
#Mann= 3 , 0 , 0
       0     .06       0   520.1    .045       0   535.1     .06       0
Bank Sta=520.1,535.1
XS Rating Curve= 0 ,0
Exp/Cntr=0.3,0.1

Type RM Length L Ch R = 1 ,15415.8 ,503.9,499.9,495.8
XS GIS Cut Line= 3
     2039041.983      315032.741     2039510.463      314635.233
     2039655.638      313997.314
#Sta/Elev= 30
       0 2478.62    20.1 2474.22    40.3 2471.53    70.5 2469.76   100.7 2469.32
   201.4 2461.52     282 2458.03   332.4 2456.54   382.7 2455.84   533.8 2456.09
   664.7 2455.33     705 2454.43   772.3 2451.52   785.5 2451.22   787.3 2451.26
   825.8 2453.34   835.8 2455.14     856 2461.22     866 2461.88   926.4 2484.84
   956.6 2495.87   966.7 2496.58  1057.3 2519.41  1077.4 2522.25  1117.6 2532.35
  1147.8 2540.47  1157.9  2542.4    1168 2543.45  1258.6 2564.31  1268.6 2564.68
#Mann= 3 , 0 , 0
       0     .06       0   772.3    .045       0   787.3     .06       0
Bank Sta=772.3,787.3
XS Rating Curve= 0 ,0
Exp/Cntr=0.3,0.1

Type RM Length L Ch R = 1 ,14915.8 ,356.7,355.5,354.3
XS GIS Cut Line= 3
     2039996.855      315460.503     2040010.528      315163.253
     2040062.057      314043.081
#Sta/Elev= 30
       0 2473.97    29.8  2474.3    69.4 2472.88    79.4 2472.21     119 2467.21
   168.6 2466.14   228.1 2461.93   277.7 2457.64   307.6  2456.4   407.7 2454.22
     688 2451.15     894 2450.92   908.3 2450.44     909 2450.52   918.3 2451.64
   938.3 2459.28   978.4 2472.15   988.4  2472.5   998.4 2475.49  1078.5 2503.29
  1088.5 2504.02  1098.5 2506.72  1168.6 2528.58  1178.6 2529.44  1188.6 2531.46
  1268.7 2551.45  1288.8 2553.39  1358.8 2563.18  1378.9 2564.49  1418.9 2569.89
#Mann= 3 , 0 , 0
       0     .06       0     894    .045       0     909     .06       0
Bank Sta=894,909
XS Rating Curve= 0 ,0
Exp/Cntr=0.3,0.1

Type RM Length L Ch R = 1 ,14559.9 ,472.7,449.1,437.9
XS GIS Cut Line= 3
     2040393.841      315449.986     2040392.168      315197.215
     2040384.686      314067.033
#Sta/Elev= 30
       0  2498.1    19.4  2494.2    29.2 2494.14    87.5 2477.69   106.9 2473.05
   116.7 2471.46   204.2 2465.18   233.3 2464.71   262.9 2463.21   313.3 2453.87
   333.5  2451.7   838.1 2448.08   838.9 2448.09   853.9 2448.75   868.3 2450.66
   888.5 2451.62   928.9 2455.65   979.3 2464.57   989.4 2464.74  1070.2 2473.13
  1080.2 2473.26  1171.1 2483.11  1181.2 2483.26  1221.5 2487.46  1261.9  2493.5
    1272 2493.68  1312.4 2501.14  1362.8 2511.72  1372.9 2511.96    1383 2514.22
#Mann= 3 , 0 , 0
       0     .06       0   838.9    .045       0   853.9     .06       0
Bank Sta=838.9,853.9
XS Rating Curve= 0 ,0
Exp/Cntr=0.3,0.1

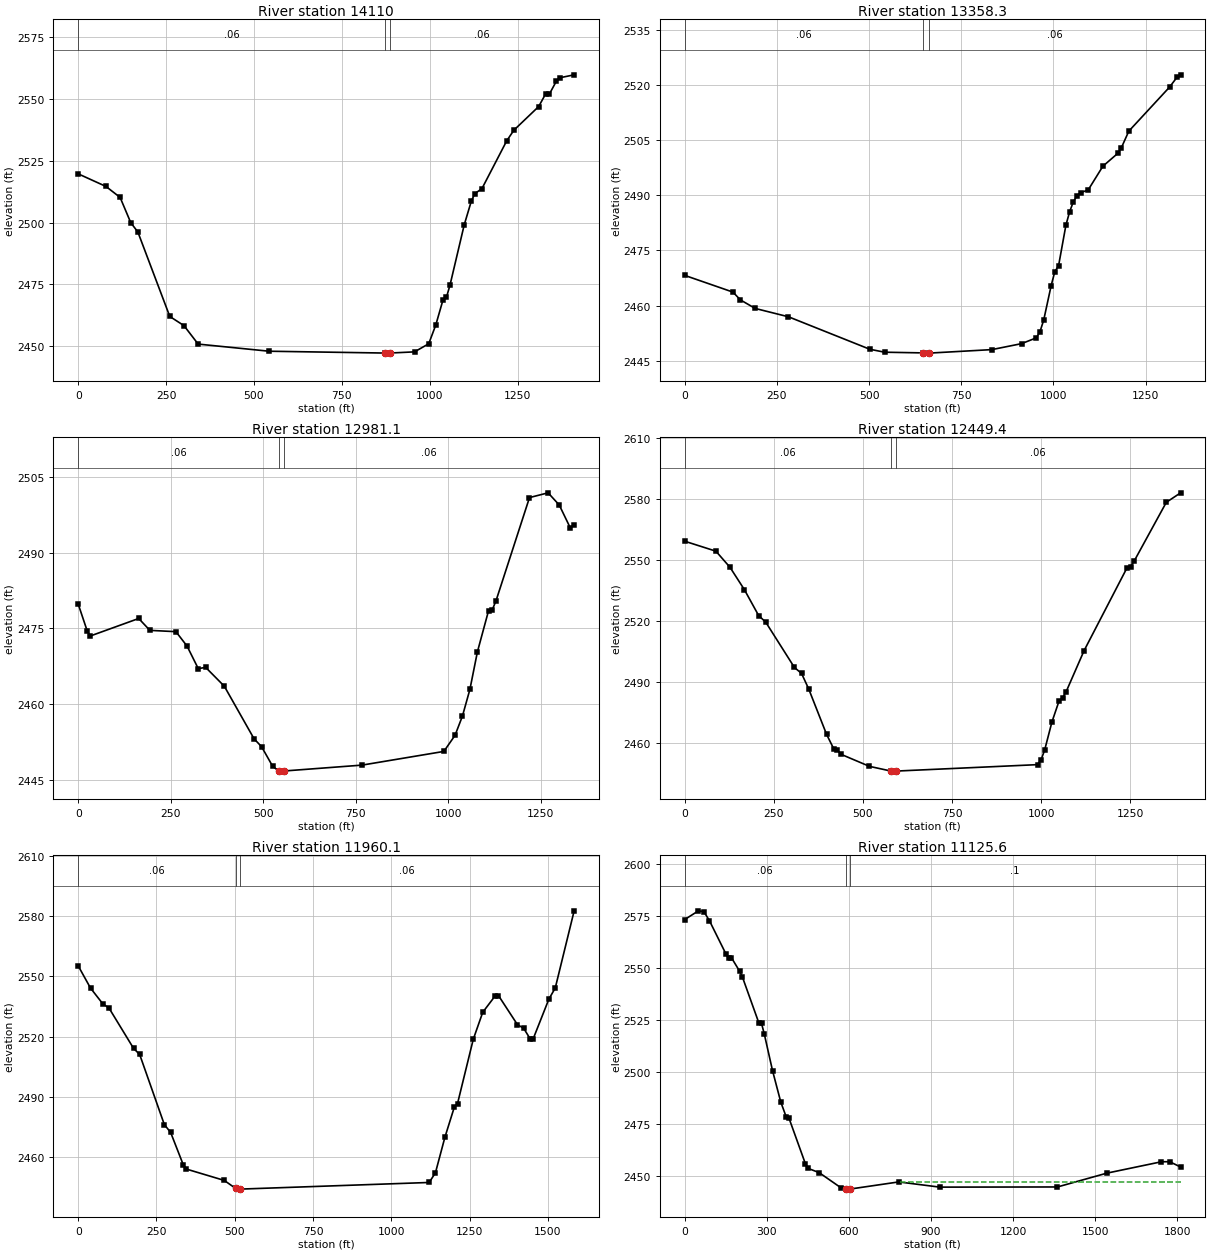
Type RM Length L Ch R = 1 ,14110   ,466.3,751.4,708.7
XS GIS Cut Line= 3
     2040953.141      315380.663     2040939.254      315323.627
     2040619.374      314009.819
#Sta/Elev= 30
       0 2519.73    78.9 2514.63   119.2 2510.18   149.5 2499.94   169.7 2496.17
   260.5 2461.95   300.9 2458.23   341.2 2450.75   543.1 2447.86   872.4 2447.12
   876.1 2447.09   887.4 2447.13   956.8  2447.6   997.2 2450.89  1017.3 2458.51
  1037.5 2468.52  1047.6 2469.73  1057.7 2474.65  1098.1 2499.03  1118.2 2508.62
  1128.3 2511.72  1148.5 2513.73  1219.2 2533.15  1239.4 2537.41    1310 2547.01
  1330.2 2552.23  1340.3 2552.04  1360.4  2557.3  1370.5 2558.67  1410.9 2559.85
#Mann= 3 , 0 , 0
       0     .06       0   872.4    .045       0   887.4     .06       0
Bank Sta=872.4,887.4
XS Rating Curve= 0 ,0
Exp/Cntr=0.3,0.1

Type RM Length L Ch R = 1 ,13358.3 ,367.3,377,382.4
XS GIS Cut Line= 3
     2041346.368      315173.127     2041328.818      315136.414
     2040766.436      313959.941
#Sta/Elev= 30
       0 2468.23     131 2463.67     151 2461.56   191.2 2459.23   281.4 2456.96
   502.1 2448.12   542.2 2447.32     647 2447.13     662 2447.07   833.1 2448.03
   913.4 2449.65   953.5 2451.23   963.5 2452.94   973.5 2456.08   993.6 2465.41
  1003.6 2469.26  1013.7 2470.81  1033.7  2481.9  1043.8 2485.55  1053.8 2488.25
  1063.8 2489.93  1073.8 2490.76  1093.9 2491.45    1134 2497.94  1174.2 2501.42
  1184.2 2502.99  1204.2 2507.47  1314.6 2519.45  1334.6  2522.1  1344.7  2522.8
#Mann= 3 , 0 , 0
       0     .06       0     647    .045       0     662     .06       0
Bank Sta=647,662
XS Rating Curve= 0 ,0
Exp/Cntr=0.3,0.1

Type RM Length L Ch R = 1 ,12981.1 ,532.2,531.3,524.4
XS GIS Cut Line= 3
     2041523.384      315079.702     2041509.262      315050.158
     2040945.349      313870.484
#Sta/Elev= 30
       0 2479.83    24.6 2474.45    32.8 2473.52   163.5 2476.98   193.7 2474.63
   264.1 2474.37   294.2 2471.51   324.4 2467.06   344.5  2467.3   394.8 2463.58
   475.3 2453.16   495.4 2451.62   525.6 2447.72     542  2446.8   545.7 2446.77
     557  2446.8     767 2447.96   988.2 2450.67  1018.4 2453.86  1038.5 2457.69
  1058.6 2462.96  1078.8 2470.36  1108.9 2478.51    1119  2478.7  1129.1 2480.48
  1219.6 2500.91  1269.9 2501.85    1300 2499.44  1330.2 2494.86  1340.3 2495.57
#Mann= 3 , 0 , 0
       0     .06       0     542    .045       0     557     .06       0
Bank Sta=542,557
XS Rating Curve= 0 ,0
Exp/Cntr=0.3,0.1

Type RM Length L Ch R = 1 ,12449.4 ,480.4,487.5,489.2
XS GIS Cut Line= 3
      2041886.89      314918.202     2041841.084      314821.354
     2041292.116      313660.657
#Sta/Elev= 30
       0 2559.15    87.6 2554.25   127.2  2546.3   167.3 2535.38   207.4 2522.62
   227.5 2519.31   307.8 2497.08   327.8 2494.14   347.9  2486.5     398 2464.18
   418.1 2457.07   428.1 2456.54   438.2  2454.4   518.4 2448.44   577.5 2446.18
   588.6  2446.1   592.5 2446.12   989.9 2449.29   999.9 2451.74  1009.9 2456.58
    1030  2470.2    1050 2480.53  1060.1  2482.1  1070.1  2485.2  1120.3 2505.34
  1240.6 2546.03  1250.7 2546.69  1260.7 2549.35    1351 2578.28  1391.1 2582.94
#Mann= 3 , 0 , 0
       0     .06       0   577.5    .045       0   592.5     .06       0
Bank Sta=577.5,592.5
XS Rating Curve= 0 ,0
Exp/Cntr=0.3,0.1

Type RM Length L Ch R = 1 ,11960.1 ,801.9,834.9,854.8
XS GIS Cut Line= 3
     2042243.854      314788.186     2042139.707      314544.482
     2041621.318      313331.455
#Sta/Elev= 30
       0 2555.25    39.3 2544.17    78.5 2536.33    98.2 2534.25   176.7 2514.13
   196.3 2511.06   275.1 2476.09   295.2 2472.18   335.5 2456.06   345.6 2453.89
   466.4 2448.24   502.6 2444.28   516.8 2443.89   517.6  2443.9    1121 2447.21
  1141.1 2452.03  1171.3 2469.74  1201.5 2484.84  1211.6 2486.52  1261.9 2518.61
  1292.2  2532.1  1332.4 2540.39  1342.5 2540.43  1402.9 2525.97  1423.1 2524.09
  1443.2 2518.98  1453.3 2518.85  1503.6 2538.73  1523.8  2544.2  1584.2 2582.71
#Mann= 3 , 0 , 0
       0     .06       0   502.6    .045       0   517.6     .06       0
Bank Sta=502.6,517.6
XS Rating Curve= 0 ,0
Exp/Cntr=0.3,0.1

Type RM Length L Ch R = 1 ,11125.6 ,340.4,326.5,313.6
XS GIS Cut Line= 3
     2042339.654      314859.877     2042656.016      314144.368
     2042558.169      313118.804
#Sta/Elev= 30
       0 2573.19    50.2 2577.39    70.2 2576.99    90.3 2572.69   150.4 2556.77
   160.5 2554.62   170.5 2554.95   200.6 2548.42   210.6 2545.74   270.8 2523.64
   280.8 2523.31   290.9 2518.25     321 2500.65     351 2485.62   371.1 2478.35
   381.1 2477.82   441.3 2455.83   451.3 2453.63   491.5 2451.61   571.7 2444.28
     588 2443.75   601.8 2443.68     603 2443.69   782.3 2447.14   932.4 2444.64
  1362.4 2444.72  1542.5 2451.34  1742.5 2456.83  1772.5 2456.86  1812.6  2454.3
#Mann= 3 , 0 , 0
       0     .06       0     588    .045       0     603      .1       0
#XS Ineff= 2 , 0
                           786.8         2447.12
Permanent Ineff=
       F       F
Bank Sta=588,603
XS Rating Curve= 0 ,0
Exp/Cntr=0.3,0.1

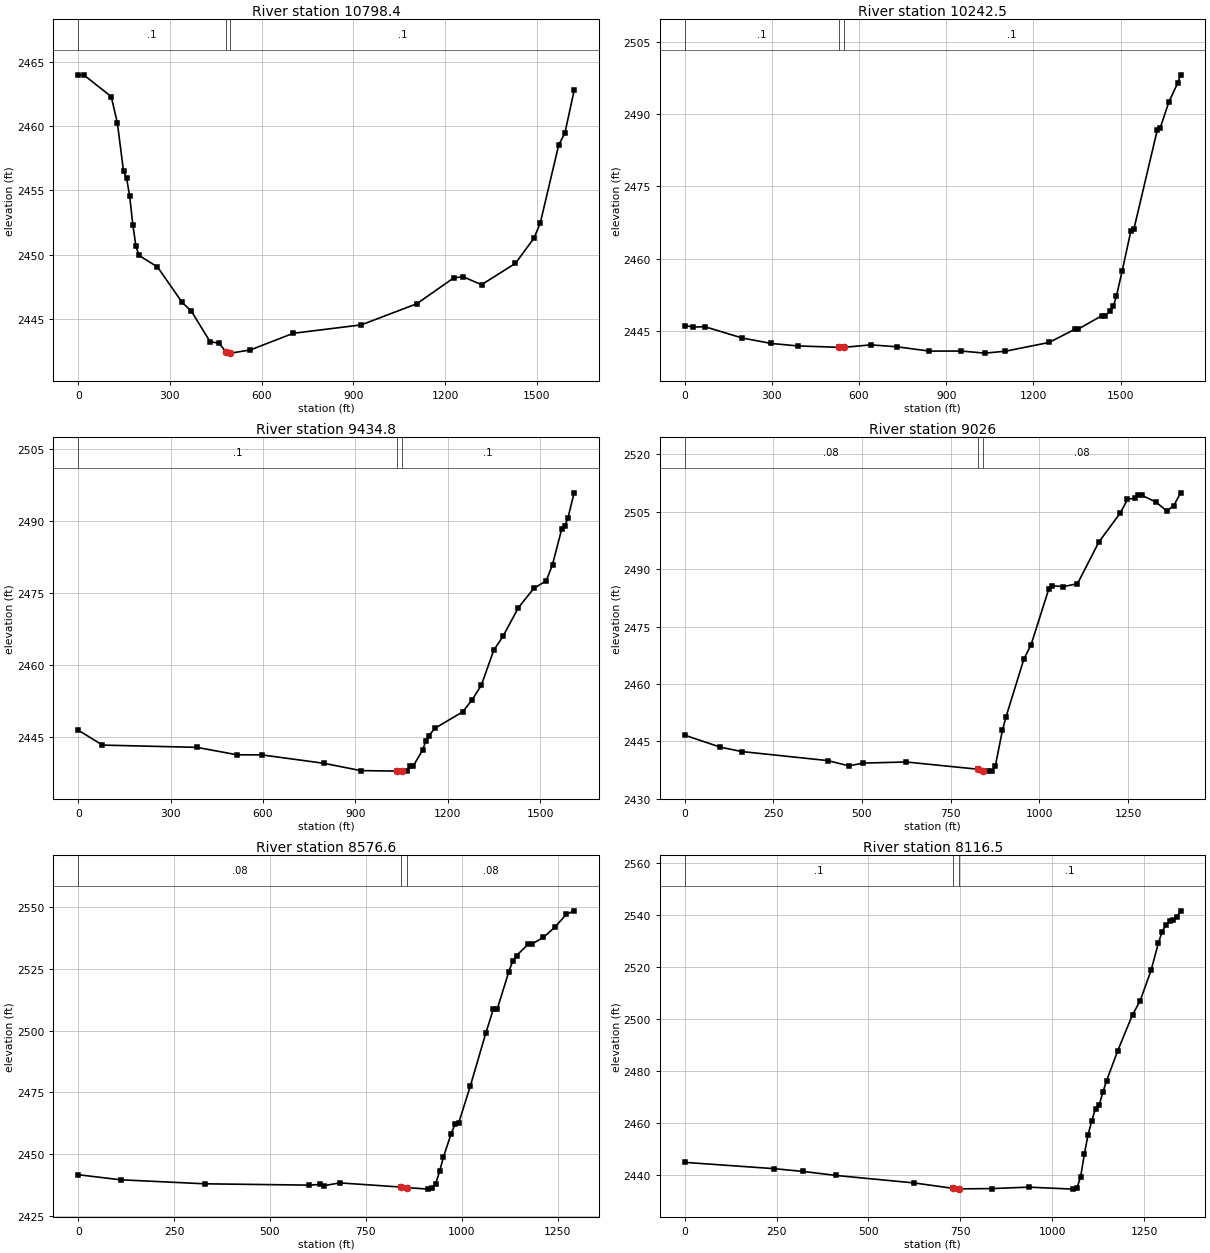
Type RM Length L Ch R = 1 ,10798.4 ,553.1,555.8,557.5
XS GIS Cut Line= 3
     2042858.396      314754.646     2042855.288      314677.125
     2042793.449      313134.394
#Sta/Elev= 30
       0 2463.97    19.4 2463.94   107.9 2462.28     128 2460.24   148.2 2456.49
   158.3 2455.93   168.4 2454.53   178.5 2452.35   188.6 2450.68   198.7 2449.95
   259.2 2449.06     340  2446.3   370.2 2445.62   430.8 2443.27     461 2443.13
   482.5 2442.48   497.5 2442.37     562 2442.61   703.2 2443.91   925.2 2444.56
  1106.9  2446.2    1228 2448.21  1258.3  2448.3  1318.8 2447.68  1429.8 2449.34
  1490.4  2451.3  1510.6 2452.45  1571.1 2458.53  1591.3 2459.45  1621.6 2462.76
#Mann= 3 , 0 , 0
       0      .1       0   482.5    .045       0   497.5      .1       0
Bank Sta=482.5,497.5
XS Rating Curve= 0 ,0
Exp/Cntr=0.3,0.1

Type RM Length L Ch R = 1 ,10242.5 ,792.4,807.8,813.1
XS GIS Cut Line= 3
     2043355.035      314895.782      2043341.84      314657.768
     2043260.554      313191.521
#Sta/Elev= 30
       0 2446.19    29.8 2445.87    69.5 2445.94   198.6 2443.59   298.7 2442.47
   389.2 2441.96   532.5 2441.67   547.5 2441.67   640.7 2442.18   731.2 2441.78
   841.9 2440.89   952.5  2440.9    1033 2440.47  1103.4 2440.86  1254.3 2442.68
  1344.8 2445.47  1354.8 2445.47  1435.3  2448.2  1445.4 2448.22  1465.5 2449.12
  1475.5 2450.21  1485.6  2452.2  1505.7 2457.46  1535.9 2465.84    1546 2466.14
  1626.4 2486.64  1636.5 2487.09  1666.6 2492.49  1696.8  2496.4  1706.9  2498.1
#Mann= 3 , 0 , 0
       0      .1       0   532.5    .045       0   547.5      .1       0
Bank Sta=532.5,547.5
XS Rating Curve= 0 ,0
Exp/Cntr=0.3,0.1

Type RM Length L Ch R = 1 ,9434.8  ,416.3,408.6,410.6
XS GIS Cut Line= 3
     2043526.101      314950.565     2043621.098      314629.424
     2043982.899      313406.345
#Sta/Elev= 30
       0  2446.5    78.8 2443.39   385.1 2442.92   515.7 2441.37     596 2441.35
   796.9 2439.61   917.4 2438.08  1035.3 2437.98  1037.9 2437.97  1050.3 2437.97
    1068 2437.98  1078.1 2438.94  1088.1 2439.04  1118.3 2442.36  1128.3 2444.16
  1138.3 2445.34  1158.4  2446.9  1248.8 2450.32  1278.9  2452.8  1309.1 2455.87
  1349.2 2463.12  1379.4 2466.04  1429.6 2472.03  1479.8 2476.04    1520  2477.6
  1540.1 2480.98  1570.2 2488.42  1580.2 2489.04  1590.3 2490.72  1610.4 2495.91
#Mann= 3 , 0 , 0
       0      .1       0  1035.3    .045       0  1050.3      .1       0
Bank Sta=1035.3,1050.3
XS Rating Curve= 0 ,0
Exp/Cntr=0.3,0.1

Type RM Length L Ch R = 1 ,9026    ,456.4,449.3,441.7
XS GIS Cut Line= 3
     2043771.426      314980.451     2044311.761      313733.152
     2044327.343      313697.183
#Sta/Elev= 30
       0 2446.65   100.7 2443.52   161.1 2442.37   402.8 2440.02   463.2 2438.64
   503.4 2439.36   624.3 2439.65   826.8 2437.76   841.8 2437.42   855.9 2437.26
   865.9 2437.38     876 2438.59   896.1 2447.98   906.2 2451.45   956.6 2466.56
   976.7 2470.25    1027 2484.91  1037.1 2485.68  1067.3 2485.46  1107.6  2486.2
    1168 2497.11  1228.4 2504.71  1248.6 2508.24  1268.7 2508.57  1278.8 2509.52
  1288.8 2509.33  1329.1 2507.54  1359.3 2505.24  1378.9 2506.56  1398.5 2509.96
#Mann= 3 , 0 , 0
       0     .08       0   826.8    .045       0   841.8     .08       0
Bank Sta=826.8,841.8
XS Rating Curve= 0 ,0
Exp/Cntr=0.3,0.1

Type RM Length L Ch R = 1 ,8576.6  ,466.5,459.9,450.9
XS GIS Cut Line= 2
     2044399.331      315160.928     2044570.342      313879.246
#Sta/Elev= 30
       0 2441.68   110.3 2439.62   330.8 2437.99   601.4 2437.46   631.5 2437.74
   641.5 2437.25   681.6 2438.37   842.2 2436.67   857.2 2436.46   912.2 2435.84
   922.2 2436.19   932.2  2438.1   942.2 2443.03   952.2 2448.86   972.3 2458.26
   982.3 2462.03   992.3 2462.78  1022.4 2477.64  1062.5 2498.92  1082.6 2508.86
  1092.6 2508.84  1122.6 2523.85  1132.7 2528.13  1142.7 2530.41  1172.8 2534.93
  1182.8 2535.09  1212.8 2537.73  1242.9 2541.95    1273 2547.14    1293 2548.52
#Mann= 3 , 0 , 0
       0     .08       0   842.2    .045       0   857.2     .08       0
Bank Sta=842.2,857.2
XS Rating Curve= 0 ,0
Exp/Cntr=0.3,0.1

Type RM Length L Ch R = 1 ,8116.5  ,496.9,487.8,482.5
XS GIS Cut Line= 2
     2045114.915      315140.952       2044666.6      313868.592
#Sta/Elev= 30
       0 2444.87   241.6 2442.46   322.2 2441.38   412.8 2439.82   624.2 2436.96
   729.9 2434.88   744.9 2434.68   835.6 2434.79   936.3 2435.34  1057.1 2434.58
  1067.1 2435.07  1077.2  2439.4  1087.3 2448.24  1097.4 2455.54  1107.4 2460.92
  1117.5 2465.56  1127.6 2466.96  1137.6 2471.86  1147.7 2476.32  1177.9 2487.74
  1218.2 2501.65  1238.3 2506.75  1268.5 2518.63  1288.6 2529.18  1298.7 2533.53
  1308.8 2536.06  1318.8 2537.48  1328.9 2537.87    1339 2539.16    1349 2541.56
#Mann= 3 , 0 , 0
       0      .1       0   729.9    .045       0   744.9      .1       0
Bank Sta=729.9,744.9
XS Rating Curve= 0 ,0
Exp/Cntr=0.3,0.1

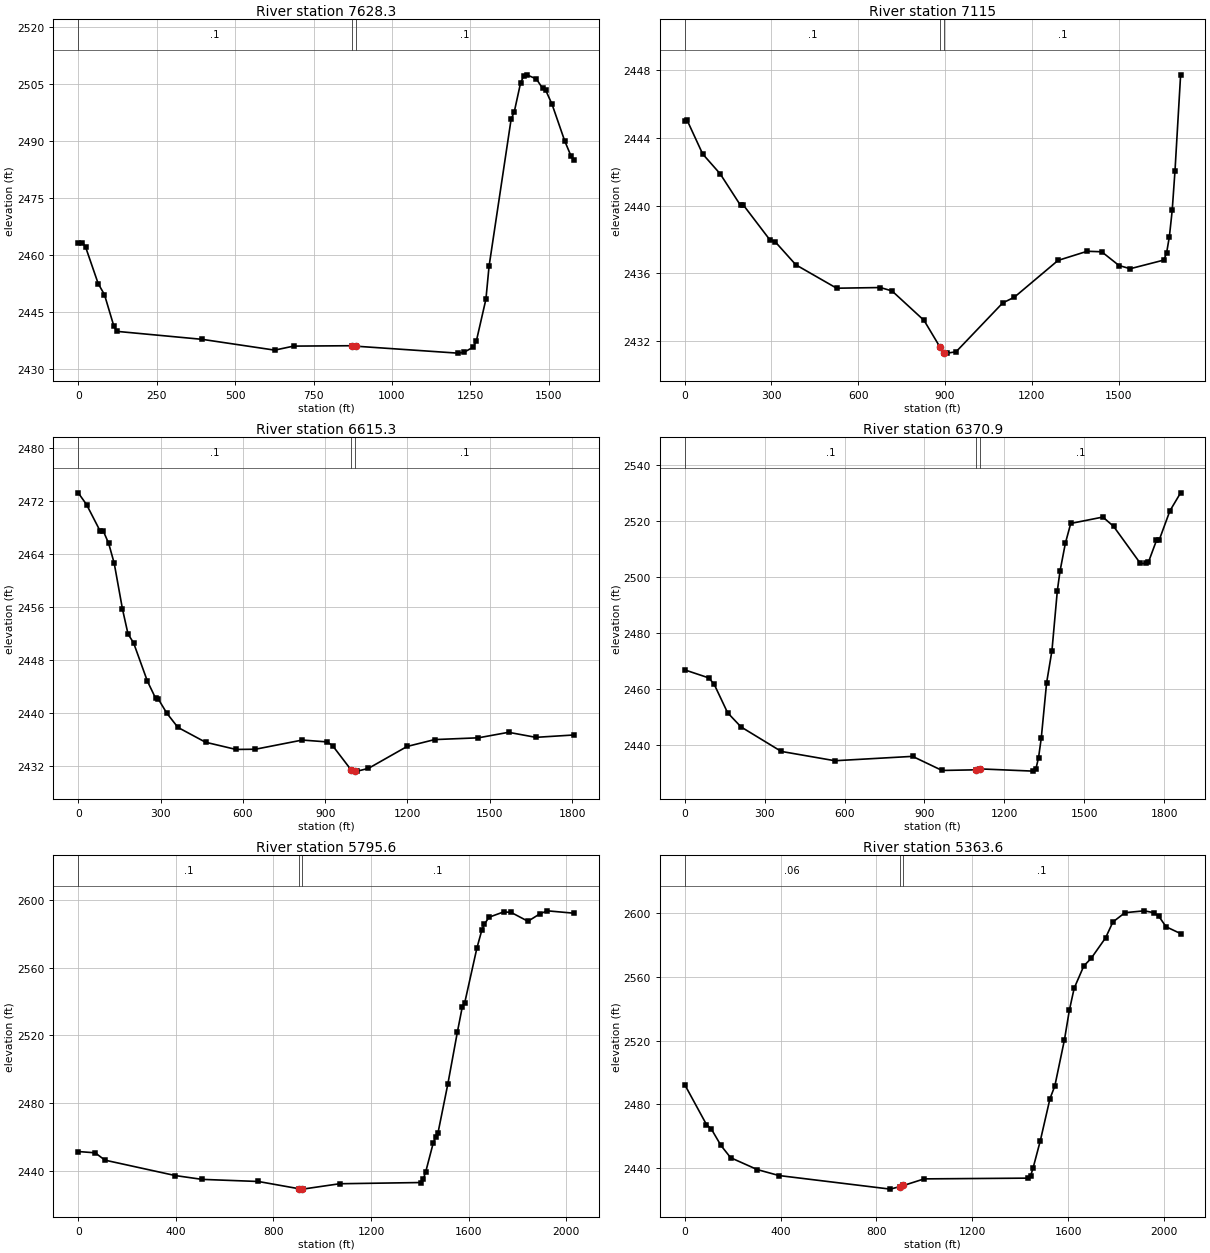
Type RM Length L Ch R = 1 ,7628.3  ,509,513.2,514.6
XS GIS Cut Line= 3
     2045506.381      315092.018      2045505.22      315088.881
     2044958.051      313609.525
#Sta/Elev= 30
       0  2463.2    13.4 2463.31    23.4 2462.15    63.6  2452.5    83.7 2449.57
   113.9  2441.2   123.9  2439.9   395.2  2437.8   626.2 2434.96   686.5 2436.02
   871.1 2436.12   886.1 2435.99  1208.9 2434.17    1229 2434.36  1259.2 2435.77
  1269.2 2437.47  1299.4 2448.38  1309.4 2457.06  1379.7  2495.8  1389.8 2497.77
  1409.9 2505.39  1419.9 2507.18    1430  2507.5  1460.1 2506.41  1480.2 2503.93
  1490.2 2503.39  1510.3  2499.7  1550.5 2490.09  1570.6  2486.1  1580.6 2484.94
#Mann= 3 , 0 , 0
       0      .1       0   871.1    .045       0   886.1      .1       0
Bank Sta=871.1,886.1
XS Rating Curve= 0 ,0
Exp/Cntr=0.3,0.1

Type RM Length L Ch R = 1 ,7115    ,507.9,499.7,490.3
XS GIS Cut Line= 4
     2045913.258      315006.753      2045895.19      314957.904
     2045399.218      313616.968     2045195.107       313505.95
#Sta/Elev= 30
       0 2444.99     8.7 2445.02    62.2 2443.04   122.6 2441.87     193 2440.01
   203.1 2440.02   293.7 2437.99   313.9 2437.84   384.3  2436.5   525.3 2435.12
   676.3 2435.16   716.6 2434.96   827.4 2433.22   882.7 2431.64   897.7  2431.3
   907.9 2431.29   938.1 2431.37  1099.2 2434.25  1139.5 2434.59  1290.5 2436.76
  1391.2  2437.3  1441.5 2437.27  1501.2 2436.46  1539.9 2436.27  1656.1 2436.78
  1665.8 2437.21  1675.4 2438.17  1685.1 2439.71  1694.8 2442.06  1714.2 2447.71
#Mann= 3 , 0 , 0
       0      .1       0   882.7    .045       0   897.7      .1       0
Bank Sta=882.7,897.7
XS Rating Curve= 0 ,0
Exp/Cntr=0.3,0.1

Type RM Length L Ch R = 1 ,6615.3  ,234.4,244.4,253.1
XS GIS Cut Line= 4
     2046431.849       314789.72     2046210.432        314161.7
     2045761.439      313686.942     2045329.392      313459.242
#Sta/Elev= 30
       0 2473.26    30.3 2471.49    80.7 2467.42    90.8 2467.54     111 2465.61
   131.2 2462.61   161.4 2455.66   181.6  2451.9   201.8 2450.57   252.2 2444.77
   282.5 2442.16   292.6 2442.02   322.9 2439.94   363.2 2437.79   464.1 2435.54
   575.1 2434.45   645.7 2434.48   816.7 2435.87   907.2 2435.59   927.3 2435.02
   994.4 2431.37  1009.4 2431.21  1017.8 2431.17    1058 2431.59  1198.7  2434.9
  1299.2 2435.94  1458.9 2436.21  1568.5 2437.04  1668.2 2436.28  1807.7 2436.64
#Mann= 3 , 0 , 0
       0      .1       0   994.4    .045       0  1009.4      .1       0
Bank Sta=994.4,1009.4
XS Rating Curve= 0 ,0
Exp/Cntr=0.3,0.1

Type RM Length L Ch R = 1 ,6370.9  ,564.8,575.3,583.9
XS GIS Cut Line= 3
     2046461.155      314770.405     2046426.167      314675.811
     2045815.372      313024.431
#Sta/Elev= 30
       0 2466.99    90.8 2464.11   110.9  2461.8   161.2 2451.67   211.5 2446.62
   362.4 2437.88   563.7 2434.55   855.4 2436.11   966.1 2431.08  1094.9 2431.31
  1109.9 2431.63  1308.2 2430.84  1318.3  2431.6  1328.3 2435.67  1338.4 2442.52
  1358.5 2462.33  1378.6 2473.84  1398.8 2495.22  1408.8 2502.17  1428.9 2512.14
  1449.1 2519.25  1569.8 2521.53    1610 2518.21  1710.7 2504.96  1730.8 2504.96
  1740.8 2505.43    1771  2513.2  1781.1 2513.31  1821.3 2523.73  1861.6 2530.18
#Mann= 3 , 0 , 0
       0      .1       0  1094.9    .045       0  1109.9      .1       0
Bank Sta=1094.9,1109.9
XS Rating Curve= 0 ,0
Exp/Cntr=0.3,0.1

Type RM Length L Ch R = 1 ,5795.6  ,441.7,432,420.1
XS GIS Cut Line= 4
     2046520.416      314725.308     2046404.734      314170.254
      2046492.87      313276.804     2046158.097      312818.213
#Sta/Elev= 30
       0 2451.38    69.6 2450.63   109.4  2446.3   397.9 2437.18   507.3 2434.93
   738.5 2433.67   903.4 2429.42   918.4 2429.17     920 2429.16  1071.4 2432.34
  1404.2 2433.06  1414.3 2435.14  1424.4 2439.48  1454.7 2456.23  1464.8 2459.96
  1474.7 2462.52  1514.6 2491.06  1554.4 2522.32  1574.3 2537.01  1584.3 2539.46
  1634.1  2571.7    1654 2582.16    1664 2585.63  1683.9  2589.9  1743.7 2593.03
  1773.6 2592.78  1843.3  2587.5  1893.1 2591.98    1923 2593.67  2032.6 2592.25
#Mann= 3 , 0 , 0
       0      .1       0   903.4    .045       0   918.4      .1       0
Bank Sta=903.4,918.4
XS Rating Curve= 0 ,0
Exp/Cntr=0.3,0.1

Type RM Length L Ch R = 1 ,5363.6  ,448.5,454.3,456.3
XS GIS Cut Line= 2
      2047159.21      314586.335     2046315.549      312696.546
#Sta/Elev= 30
       0 2492.45    90.9 2467.35     111 2464.59   151.4  2454.2   191.8 2446.52
   302.9 2439.07   393.7 2435.32   858.1  2426.8   898.1  2428.4   913.1 2429.08
   999.4 2433.23  1433.6  2433.7  1443.6 2435.18  1453.7 2439.92    1484 2457.13
  1524.4  2483.6  1544.6 2491.51    1585 2520.67  1605.2    2539  1625.4 2552.91
  1665.7 2566.92    1696 2571.59  1756.6 2584.55  1786.9 2594.47  1837.4 2600.32
  1918.1 2601.48  1958.5 2600.29  1978.7 2598.03    2009 2591.46  2069.6 2587.19
#Mann= 3 , 0 , 0
       0     .06       0   898.1    .045       0   913.1      .1       0
Bank Sta=898.1,913.1
XS Rating Curve= 0 ,0
Exp/Cntr=0.3,0.1