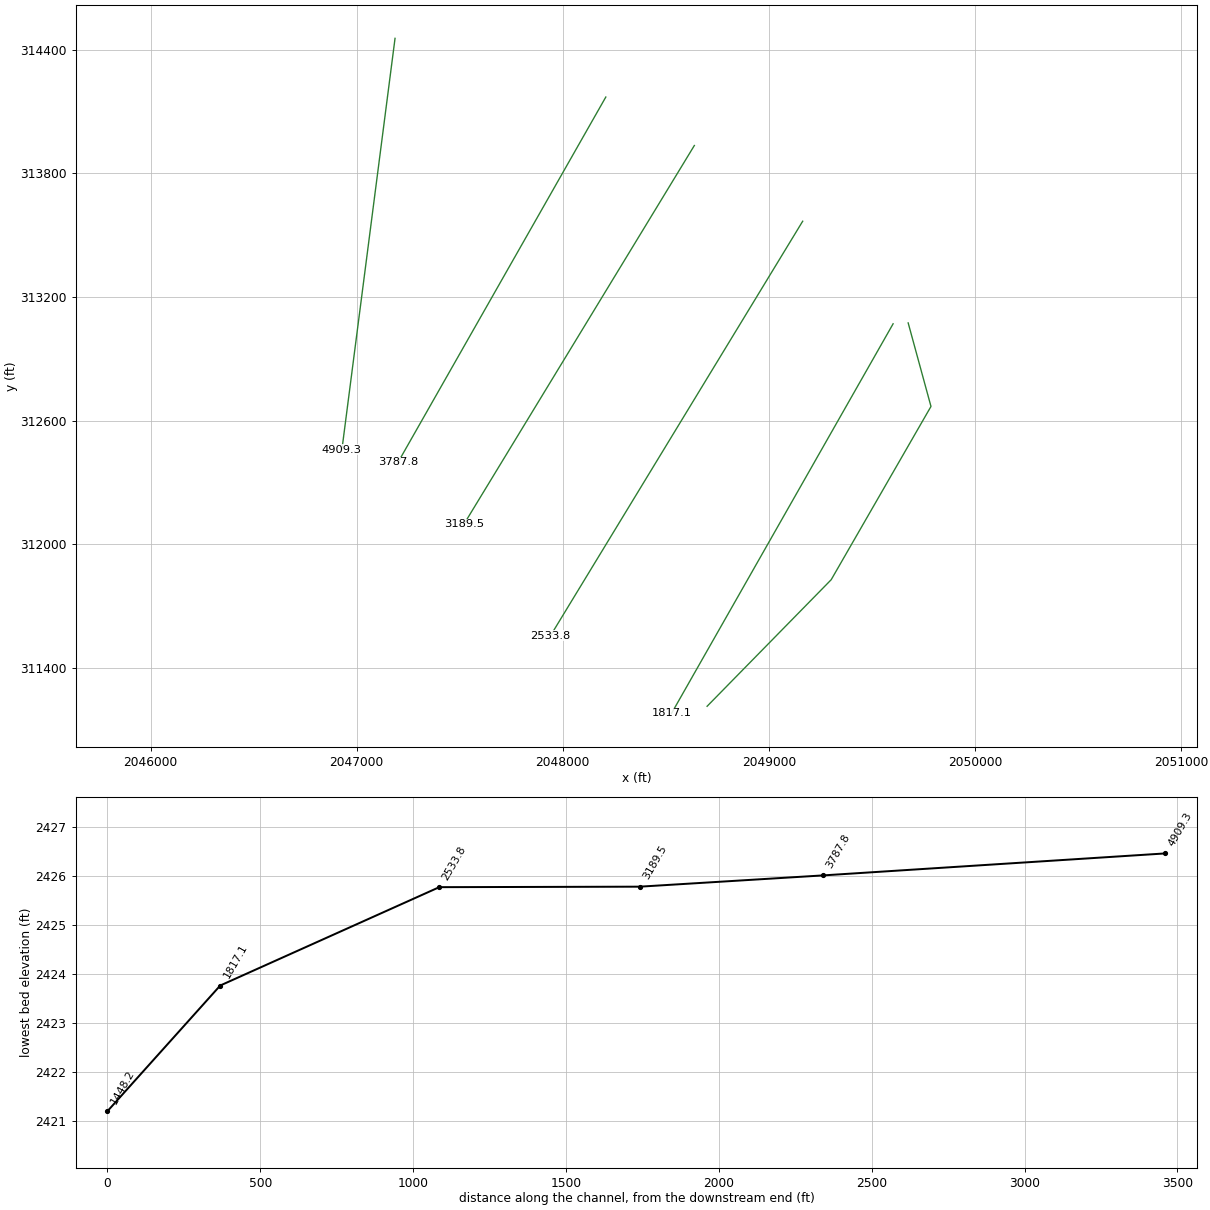
HEC-RAS study BuffaloCk.prj: BuffaloCk

--- BuffaloCk.g01 (geometry) --- (continued)

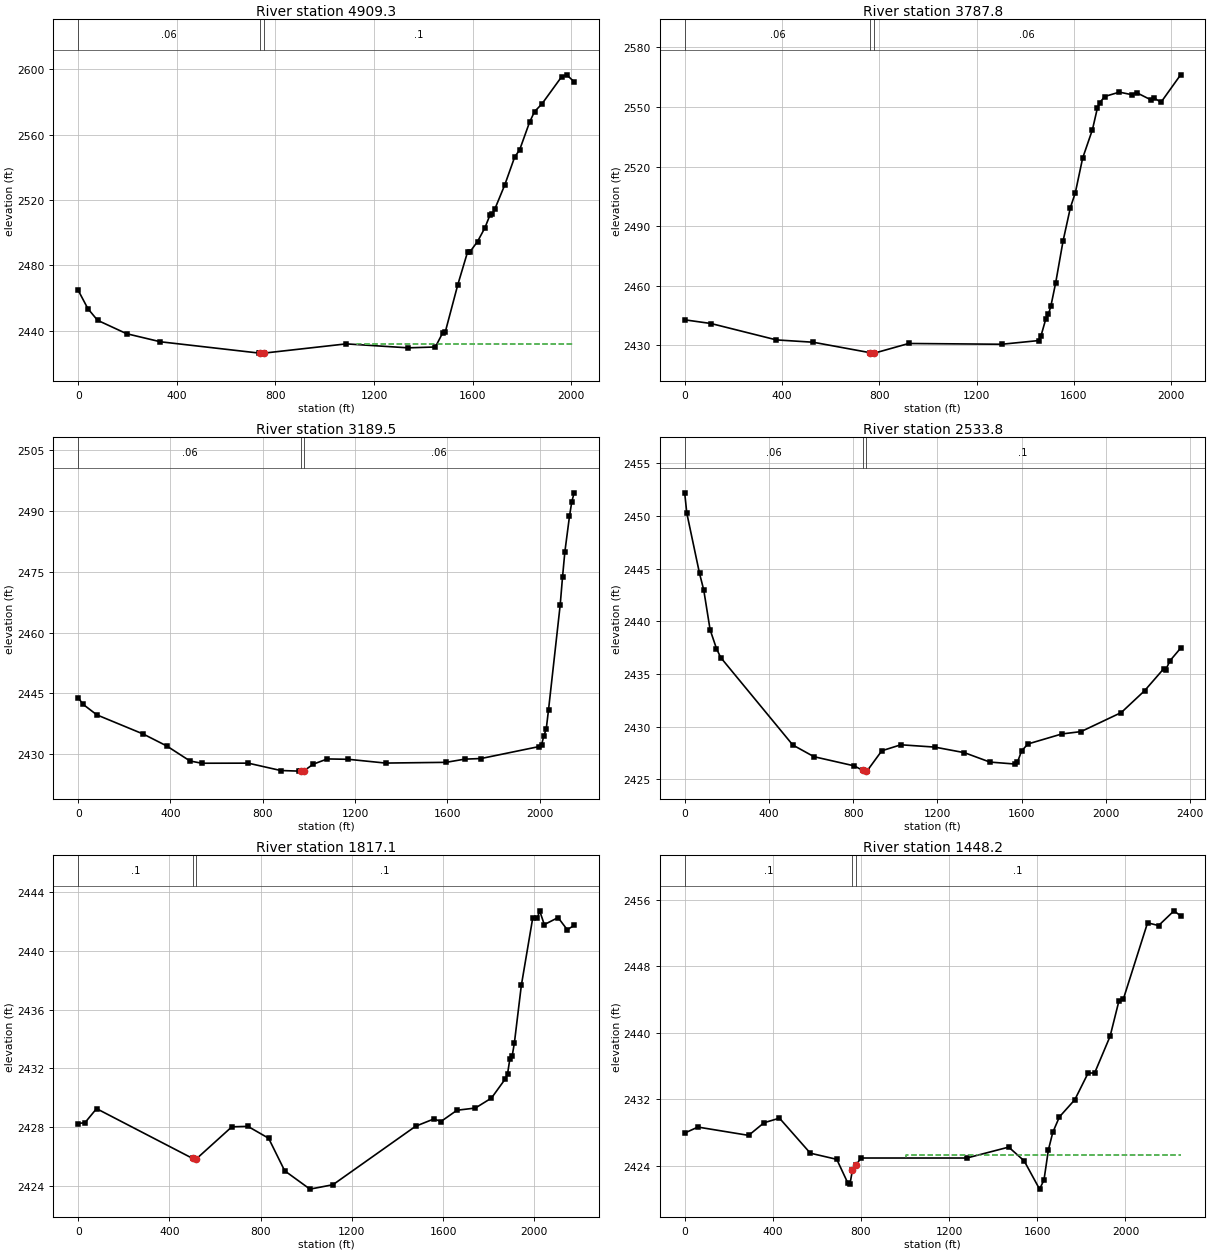
Type RM Length L Ch R = 1 ,4909.3  ,1131.8,1121.1,1118.9
XS GIS Cut Line= 3
     2047186.081      314454.204     2047142.083      314113.616
     2046928.279      312458.587
#Sta/Elev= 30
       0 2464.82    39.2 2453.64    78.5 2446.53   196.2 2438.34   333.6  2433.4
   735.5 2426.47   738.2 2426.47   753.2 2426.47  1087.3 2432.12  1338.7  2429.7
  1449.2 2430.22  1479.4 2439.02  1489.4 2439.45  1539.7 2468.04  1579.9 2488.34
    1590 2488.48  1620.1 2494.62  1650.3 2503.08  1670.4 2510.75  1680.4 2511.47
  1690.5 2514.52  1730.7 2529.24  1770.9 2546.27    1791 2550.63  1831.2 2567.49
  1851.4 2573.99  1881.5 2578.71  1961.9  2595.4    1982 2596.47  2012.2  2592.2
#Mann= 3 , 0 , 0
       0     .06       0   738.2    .045       0   753.2      .1       0
#XS Ineff= 2 , 0
                         1129.81         2432.27
Permanent Ineff=
       F       F
Bank Sta=738.2,753.2
XS Rating Curve= 0 ,0
Exp/Cntr=0.3,0.1

Type RM Length L Ch R = 1 ,3787.8  ,619.7,598.4,600.1
XS GIS Cut Line= 3
     2048208.656       314169.35      2048096.86      313972.806
      2047200.41      312396.787
#Sta/Elev= 30
       0  2442.8   108.1 2440.94   377.2 2432.68   528.3 2431.51   762.6 2426.23
   777.6 2426.03   780.1 2426.02   921.2 2430.88  1303.9 2430.49    1455 2432.34
  1465.1 2434.71  1485.2 2443.38  1495.3 2445.51  1505.4 2449.53  1525.5 2461.46
  1555.8 2482.49    1586 2499.37  1606.1 2506.76  1636.3 2524.24  1676.6 2538.61
  1696.8 2549.38  1706.8 2552.19    1727 2555.31  1787.4 2557.51  1837.8 2556.24
  1857.9 2557.26  1918.4 2553.54  1928.4 2554.68  1958.7 2552.43  2039.2 2566.23
#Mann= 3 , 0 , 0
       0     .06       0   762.6    .045       0   777.6     .06       0
Bank Sta=762.6,777.6
XS Rating Curve= 0 ,0
Exp/Cntr=0.3,0.1

Type RM Length L Ch R = 1 ,3189.5  ,655.9,655.7,655.5
XS GIS Cut Line= 2
     2048638.278      313934.274     2047520.636      312097.454
#Sta/Elev= 30
       0 2443.93    20.2 2442.32    80.8 2439.68   282.6 2434.93   383.6 2432.01
   484.5  2428.3     535 2427.74   736.9 2427.76   878.2 2425.94     959 2425.79
   965.4 2425.81   980.4 2425.94  1019.5 2427.52  1080.1  2428.8    1171 2428.71
  1332.5 2427.78  1594.9 2427.96  1675.7 2428.75  1746.3  2428.9  1998.7 2431.86
  2008.8 2432.29  2018.9 2434.53    2029 2436.16  2039.1 2440.98  2089.6 2466.83
  2099.6 2473.65  2109.8 2479.93  2129.9 2488.72    2140 2492.34  2150.1  2494.5
#Mann= 3 , 0 , 0
       0     .06       0   965.4    .045       0   980.4     .06       0
Bank Sta=965.4,980.4
XS Rating Curve= 0 ,0
Exp/Cntr=0.3,0.1

Type RM Length L Ch R = 1 ,2533.8  ,715.5,716.4,717.4
XS GIS Cut Line= 2
     2049163.959      313566.953     2047940.085      311555.541
#Sta/Elev= 30
       0 2452.19    10.1 2450.26    70.4 2444.55    90.6 2442.96   120.7  2439.2
   150.9 2437.41     171 2436.56   513.2 2428.26   613.8 2427.15     805 2426.28
   845.2 2425.85   860.2 2425.81   865.3 2425.78   935.8 2427.71  1026.3 2428.28
  1187.3 2428.06  1328.2 2427.53  1448.9 2426.64  1569.7 2426.45  1579.7 2426.62
  1599.8 2427.71    1630 2428.36    1791 2429.31  1881.6 2429.53  2072.8 2431.34
  2183.4 2433.41    2274 2435.49  2284.1 2435.41  2304.2 2436.26  2354.5 2437.45
#Mann= 3 , 0 , 0
       0     .06       0   845.2    .045       0   860.2      .1       0
Bank Sta=845.2,860.2
XS Rating Curve= 0 ,0
Exp/Cntr=0.3,0.1

Type RM Length L Ch R = 1 ,1817.1  ,369.2,369.1,368.9
XS GIS Cut Line= 3
     2049602.563      313069.122     2049359.166      312641.213
     2048527.485      311179.064
#Sta/Elev= 30
       0 2428.24    30.1 2428.31    80.4 2429.26   502.1 2425.86   517.1 2425.82
   673.6 2428.02   744.1 2428.05   834.8 2427.24   905.3 2425.02  1016.1 2423.77
  1116.8 2424.07  1479.4 2428.06    1560 2428.56  1590.2 2428.38  1660.7 2429.15
  1741.3  2429.3  1811.8 2429.98  1872.2 2431.28  1882.3 2431.62  1892.4 2432.64
  1902.5 2432.83  1912.5 2433.76  1942.8 2437.66  1993.1 2442.29  2013.3 2442.28
  2023.3 2442.75  2043.5 2441.81  2103.9 2442.29  2144.2 2441.46  2174.4 2441.76
#Mann= 3 , 0 , 0
       0      .1       0   502.1    .045       0   517.1      .1       0
Bank Sta=502.1,517.1
XS Rating Curve= 0 ,0
Exp/Cntr=0.3,0.1

Type RM Length L Ch R = 1 ,1448.2  ,1390.2,1448.3,1502.9
XS GIS Cut Line= 4
     2049675.677      313073.511     2049786.329      312668.245
     2049302.203      311827.615      2048700.11       311213.48
#Sta/Elev= 30
       0 2427.94      60 2428.66   290.1 2427.66   360.1 2429.18   430.1 2429.73
   570.1 2425.52   690.1 2424.78   740.1 2421.94   750.1 2421.81   760.9 2423.47
   775.9 2424.05   800.1 2424.94  1280.2 2424.94  1470.2 2426.25  1540.2  2424.6
  1610.2  2421.2  1630.2 2422.29  1650.2 2425.91  1670.2 2428.02  1700.2 2429.88
  1770.2 2431.95  1830.2 2435.14  1860.2 2435.17  1930.2 2439.57  1970.2 2443.81
  1990.2 2444.03  2100.2 2453.21  2150.2 2452.88  2220.2 2454.65  2250.2 2454.04
#Mann= 3 , 0 , 0
       0      .1       0   760.9    .045       0   775.9      .1       0
#XS Ineff= 2 , 0
                         1002.43         2425.31
Permanent Ineff=
       F       F
Bank Sta=760.9,775.9
XS Rating Curve= 0 ,0
Exp/Cntr=0.3,0.1

Chan Stop Cuts=-1
Use User Specified Reach Order=0
Composite Channel Slope=5